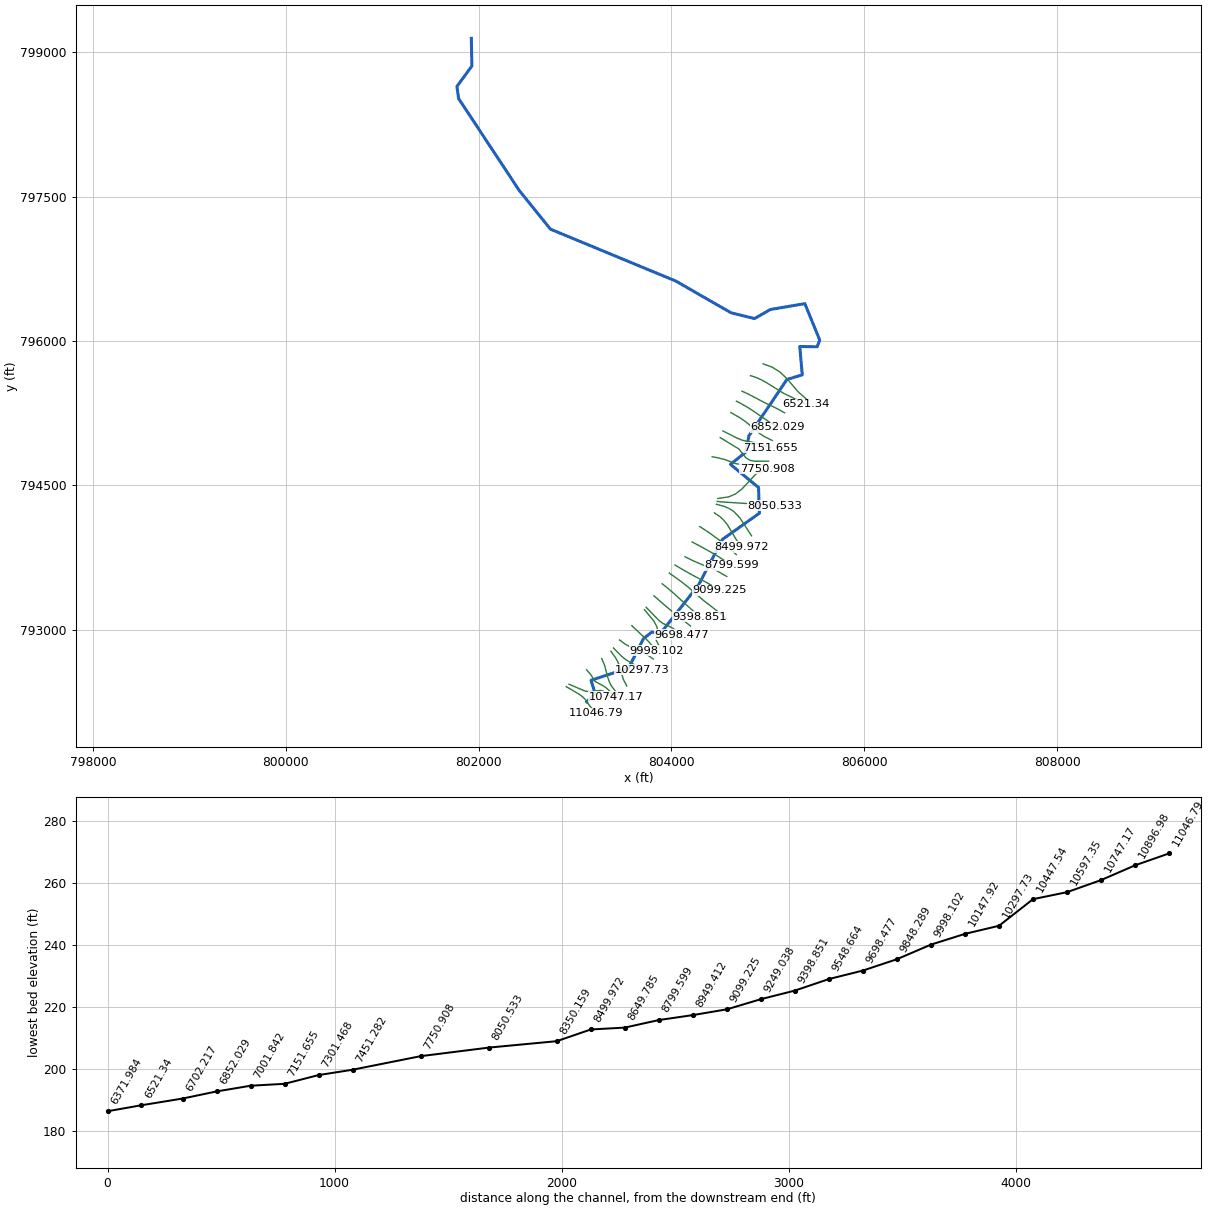
--- 17439_ras.prj (project) ---

Proj Title=17439
Current Plan=p01
Default Exp/Contr=0.3,0.1
English Units
Geom File=g01
Flow File=f01
Plan File=p01
Y Axis Title=Elevation
X Axis Title(PF)=Main Channel Distance
X Axis Title(XS)=Station
BEGIN DESCRIPTION:
RFD model 17439 exported to HEC-RAS
END DESCRIPTION:

--- 17439_ras.p01 (plan) ---

Plan Title=Plan 01
Program Version=4.10
Short Identifier=Plan 01
Geom File=g01
Flow File=f01
Subcritical Flow
Calc Critical at every XS
Secant Critical Depth

--- 17439_ras.f01 (steady flow) ---

Flow Title=Flow 01
Program Version=5.01
Number of Profiles= 6
Profile Names=10yr,25yr,50yr,100yr,100plus,500yr
River Rch & RM=17439,41,11046.79
  872.86 1383.81 1859.57 2284.42 3335.25 4533.17
River Rch & RM=17439,41,10896.98
  874.82 1387.02 1863.97 2289.91 3343.27 4542.93
River Rch & RM=17439,41,10747.17
  877.34 1391.14 1869.62 2296.97 3353.58 4555.48
River Rch & RM=17439,41,10597.35
  882.37 1399.36 1880.91 2311.08 3374.18 4580.52
River Rch & RM=17439,41,10447.54
  886.56 1406.21 1890.31 2322.82 3391.32 4601.35
River Rch & RM=17439,41,10297.73
  888.79 1409.86 1895.31 2329.08 3400.46 4612.45
River Rch & RM=17439,41,10147.92
  891.58 1414.42 1901.57  2336.9 3411.88  4626.3
River Rch & RM=17439,41,9998.102
  899.65 1427.63 1919.69 2359.54 3444.93 4666.39
River Rch & RM=17439,41,9848.289
  903.25 1433.52 1927.78 2369.66 3459.71 4684.32
River Rch & RM=17439,41,9698.477
  905.19  1436.7 1932.14 2375.12 3467.67 4693.96
River Rch & RM=17439,41,9548.664
  906.84 1439.41 1935.86 2379.77 3474.46 4702.21
River Rch & RM=17439,41,9398.851
     910 1444.66 1943.13 2388.92 3487.83 4718.71
River Rch & RM=17439,41,9249.038
  911.31 1446.83 1946.14 2392.73 3493.39 4725.58
River Rch & RM=17439,41,9099.225
  982.72 1564.16  2107.6 2595.02 3788.73 5082.86
River Rch & RM=17439,41,8949.412
  983.99 1566.28 2110.54 2598.75 3794.17 5089.53
River Rch & RM=17439,41,8799.599
  985.26 1568.41 2113.49 2602.47 3799.61 5096.19
River Rch & RM=17439,41,8649.785
  988.06 1573.08 2119.98 2610.66 3811.57 5110.85
River Rch & RM=17439,41,8499.972
  989.59 1575.62 2123.51 2615.13 3818.09 5118.83
River Rch & RM=17439,41,8350.159
  991.62 1579.02 2128.23 2621.08 3826.78 5129.48
River Rch & RM=17439,41,8050.533
 1003.94 1599.49 2156.61 2656.87 3879.03 5193.14
River Rch & RM=17439,41,7750.908
 1007.49 1605.41 2164.83 2667.25 3894.18 5211.65
River Rch & RM=17439,41,7451.282
 1015.57  1618.9 2183.56 2690.92 3928.74 5253.87
River Rch & RM=17439,41,7301.468
 1016.31 1620.13 2185.29 2693.11 3931.94 5257.82
River Rch & RM=17439,41,7151.655
 1018.04 1623.04 2189.34 2698.25 3939.44 5267.03
River Rch & RM=17439,41,7001.842
 1024.69 1634.21 2204.92 2718.01 3968.29 5302.51
River Rch & RM=17439,41,6852.029
 1027.87 1639.57  2212.4 2727.49 3982.14 5319.56
River Rch & RM=17439,41,6702.217
 1032.52 1647.39 2223.32 2741.35 4002.37 5344.44
River Rch & RM=17439,41, 6521.34
 1053.38 1682.29 2271.89  2802.8 4092.09  5453.9
River Rch & RM=17439,41,6371.984
 1057.52 1689.25  2281.6 2815.13 4110.09 5475.95
River Rch & RM=17439,41,6073.272
 1059.23 1692.11  2285.6  2820.2  4117.5 5485.02
River Rch & RM=17439,41,5923.916
 1060.69 1694.57 2289.03 2824.55 4123.84 5492.79
River Rch & RM=17439,41,5625.204
 1063.61 1699.48 2295.88 2833.24 4136.54 5508.31
River Rch & RM=17439,41,5475.848
 1064.58 1701.11 2298.16 2836.14 4140.76 5513.48
Boundary for River Rch & Prof#=17439,41,1
Up Type= 0
Dn Type= 2
Boundary for River Rch & Prof#=17439,41,2
Up Type= 0
Dn Type= 2
Boundary for River Rch & Prof#=17439,41,2
Up Type= 0
Dn Type= 2
Boundary for River Rch & Prof#=17439,41,2
Up Type= 0
Dn Type= 2
Boundary for River Rch & Prof#=17439,41,2
Up Type= 0
Dn Type= 2
Boundary for River Rch & Prof#=17439,41,2
Up Type= 0
Dn Type= 2

--- 17439_ras.g01 (geometry) ---

Geom Title=17439
Program Version=4.10

River Reach=17439,41
Reach XY= 30
803121.257483096792250.373983225803207.244518075 792336.55089174
803165.768669518792473.949305583803554.381271842792600.379819221
803709.731951297792907.006339894803795.076989177792973.920335804
803886.098912747792961.009424676804281.290306598793465.246798574
804527.692443255793937.259069554804911.898782315 794209.77474998
804902.829960703794476.379832854804611.692118737794716.893339605
 804770.25727272 794844.68624564804802.383705616795012.737768555
805197.067011059795599.201972059805356.006145925795647.124487211
805330.294642269795941.897218227805510.428027513795939.123321132
805537.478297654796008.215133096805383.119925291796387.137318707
805024.908254028796326.257184473804861.713809609796232.507184482
804618.658254059796291.534962254  804045.7415874796621.396073369
802744.936131122797160.869983251 802420.43588567797564.047255668
801792.174538466798518.628384479801774.641160012 798643.56487677
801930.089877993798856.705902439801924.235270949799143.898199191

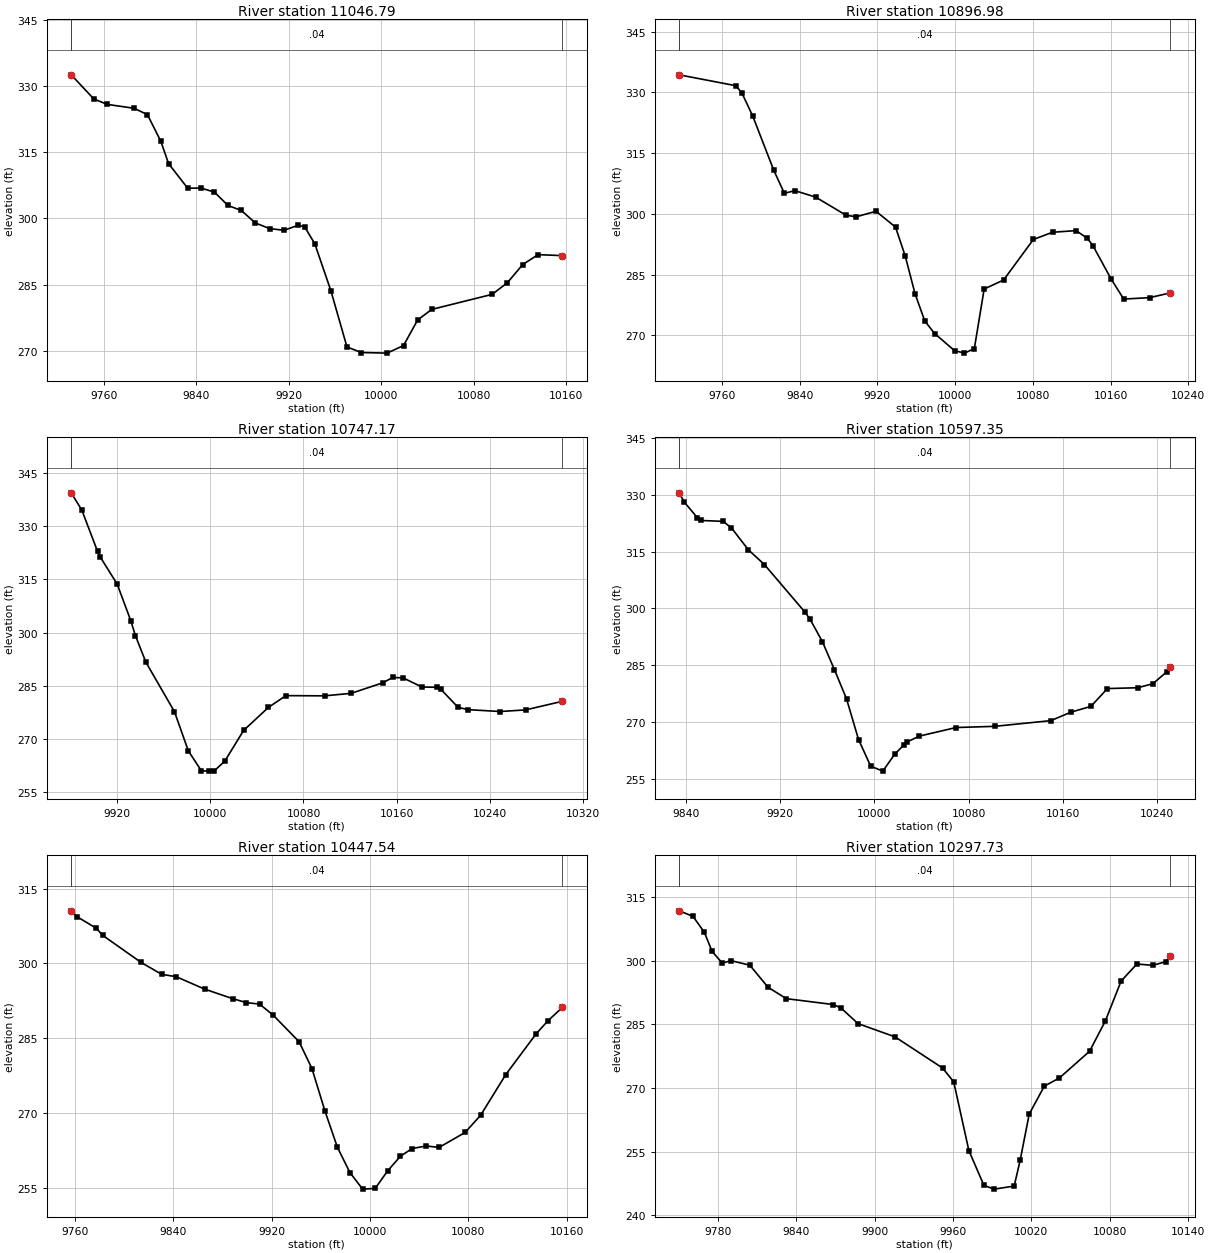
Type RM Length L Ch R = 1 ,11046.79,149.813000,149.813000,149.813000
XS GIS Cut Line= 6
802908.195978185792407.667349011803038.820647045792330.887325992
803079.540702002792301.341160069803105.624815104792274.344714435
803150.509187112792210.076847474803221.317135789792129.805293831
#Sta/Elev= 30
 9731.97332.59039751.461327.12419763.061325.8856 9786.26325.0044 9797.86 323.565
9809.459317.5036 9816.17312.43559832.658306.86919844.258306.89379855.858305.9694
9867.457302.95269879.057301.81499891.123298.98959903.478297.70919915.833297.3111
9928.188298.44829933.798298.11479942.616294.25299956.521283.59579970.426 270.844
9982.778269.584510005.14269.442810019.35 271.16910031.54 276.95910043.73279.3636
10096.01282.7794 10109.2285.4335 10122.4289.5376 10135.7 291.789 10156.8291.5631
#Mann= 3 , 0 , 0
 9731.97    0.04       0 9731.97    0.04       0 10156.8    0.04       0
#XS Ineff= 2 , 0
       0                               0
Bank Sta=9731.97,10156.8
Exp/Cntr=0.3,0.1

Type RM Length L Ch R = 1 ,10896.98,149.813000,149.813000,149.813000
XS GIS Cut Line= 6
802937.747444898792432.319090673803103.882779019792361.512304901
803151.438312951 792355.01714058803259.450882731792367.749257618
803291.160883453792360.492906562803400.891813621792283.861464807
#Sta/Elev= 30
 9715.93334.31749774.402331.62249780.685329.73449791.594324.16289813.331310.7365
9824.199305.06269835.068 305.7239856.461304.12239887.782299.63779898.193299.2758
9918.547300.6322 9938.65296.71159948.682289.53279958.701280.29179968.721273.5586
9978.861270.45469999.391 266.22410009.59265.611710019.77266.734610029.87281.4366
10049.87 283.66110080.53293.667810100.33295.455410124.49295.851910136.17293.9444
10141.83292.144510160.76283.834410173.55278.957610200.35279.312610221.64280.4953
#Mann= 3 , 0 , 0
 9715.93    0.04       0 9715.93    0.04       010221.64    0.04       0
#XS Ineff= 2 , 0
       0                               0
Bank Sta=9715.93,10221.64
Exp/Cntr=0.3,0.1

Type RM Length L Ch R = 1 ,10747.17,149.813000,149.813000,149.813000
XS GIS Cut Line= 6
803118.723587553792583.288826251 803164.96552715792529.909531652
803204.346909159792463.806682511803297.783406158792412.123761861
803326.508307688792392.062402623803422.527288736792302.422425036
#Sta/Elev= 30
9880.783339.45669889.926334.53689903.385 322.8989905.797321.26299920.214313.6705
 9931.81303.38489935.852299.11729944.816291.61719969.316277.64979981.259266.5546
9992.412260.9489    9999260.855310003.51260.953910012.48263.671510028.63272.3466
10049.92278.8526 10064.9282.179610098.03282.118310120.85282.823710148.05 285.804
10156.61287.324110165.52287.177110181.56284.612710194.42284.532410197.74 283.986
 10212.6278.869110221.33278.212710248.68277.694710270.51278.147210302.13280.5846
#Mann= 3 , 0 , 0
9880.783    0.04       09880.783    0.04       010302.13    0.04       0
#XS Ineff= 2 , 0
       0                               0
Bank Sta=9880.783,10302.13
Exp/Cntr=0.3,0.1

Type RM Length L Ch R = 1 ,10597.35,149.813000,149.813000,149.813000
XS GIS Cut Line= 6
803276.851505495792698.849778125803307.325870002792626.024916484
803337.218826118792508.346505638803362.188801172792441.372173222
803379.665121664792411.301491327803447.076706364792323.483241211
#Sta/Elev= 30
9834.021330.53369838.314 328.1039849.464323.9471 9852.44323.22189871.329322.9939
9878.458321.25719892.734315.50799906.517311.54189940.801299.04939945.326297.0795
9955.717291.21419965.989283.78319976.261276.07599986.533265.27389996.805258.2759
10007.08256.963310017.36261.4818   10025263.881610027.65264.6529   10038266.2059
10069.45268.492210102.11268.799310149.96270.310810167.02272.551810184.08274.0836
10198.01278.787810223.77279.007410236.71280.066210248.35283.183210251.62284.4331
#Mann= 3 , 0 , 0
9834.021    0.04       09834.021    0.04       010251.62    0.04       0
#XS Ineff= 2 , 0
       0                               0
Bank Sta=9834.021,10251.62
Exp/Cntr=0.3,0.1

Type RM Length L Ch R = 1 ,10447.54,149.813000,149.813000,149.813000
XS GIS Cut Line= 6
803372.226360888792775.301256007803422.429562675 792702.74498326
803445.757203213792659.919637149803461.139733171792623.181216956
803500.015033475792484.163457911803536.038796013792414.705292109
#Sta/Elev= 30
9756.879310.52999761.399309.38139777.352307.03049782.324305.64199813.757300.1727
9830.417297.8004 9842.44297.30629865.358294.83349888.133292.91999899.251292.1291
9910.093291.81829920.934289.66969942.298284.2706 9952.75278.89669963.202270.4705
9973.493263.06759983.737258.00359993.981254.709210004.22254.8501 10014.5258.4268
10024.79261.308710034.18262.847110045.67263.362910056.24263.080610077.37266.0727
10090.03269.536610110.45277.6818 10135.1285.8412 10144.6288.4316 10156.6 291.182
#Mann= 3 , 0 , 0
9756.879    0.04       09756.879    0.04       0 10156.6    0.04       0
#XS Ineff= 2 , 0
       0                               0
Bank Sta=9756.879,10156.6
Exp/Cntr=0.3,0.1

Type RM Length L Ch R = 1 ,10297.73,149.813000,149.813000,149.813000
XS GIS Cut Line= 6
803397.776056616792809.109439244803483.309932415792722.499344863
 803507.48444914792702.108582931803531.899314883792684.189791894
803644.989063875792618.361788591803695.774716063792582.806133766
#Sta/Elev= 30
9750.101311.74299760.687310.44139769.403306.66369775.341302.15769783.084299.4441
9789.995299.98429804.221298.92979818.221293.71449832.221291.03889868.283289.6454
9874.067288.85539887.149285.15569915.496282.03639951.962274.69099960.531271.4122
9972.118255.23699983.704246.99359991.561 246.13710006.86246.858310011.46252.9728
10018.41263.845410029.97 270.41710041.52272.337910064.63278.633310076.73285.7731
10088.82295.186610100.92299.204310113.08 298.89510123.02299.749610126.63301.1233
#Mann= 3 , 0 , 0
9750.101    0.04       09750.101    0.04       010126.63    0.04       0
#XS Ineff= 2 , 0
       0                               0
Bank Sta=9750.101,10126.63
Exp/Cntr=0.3,0.1

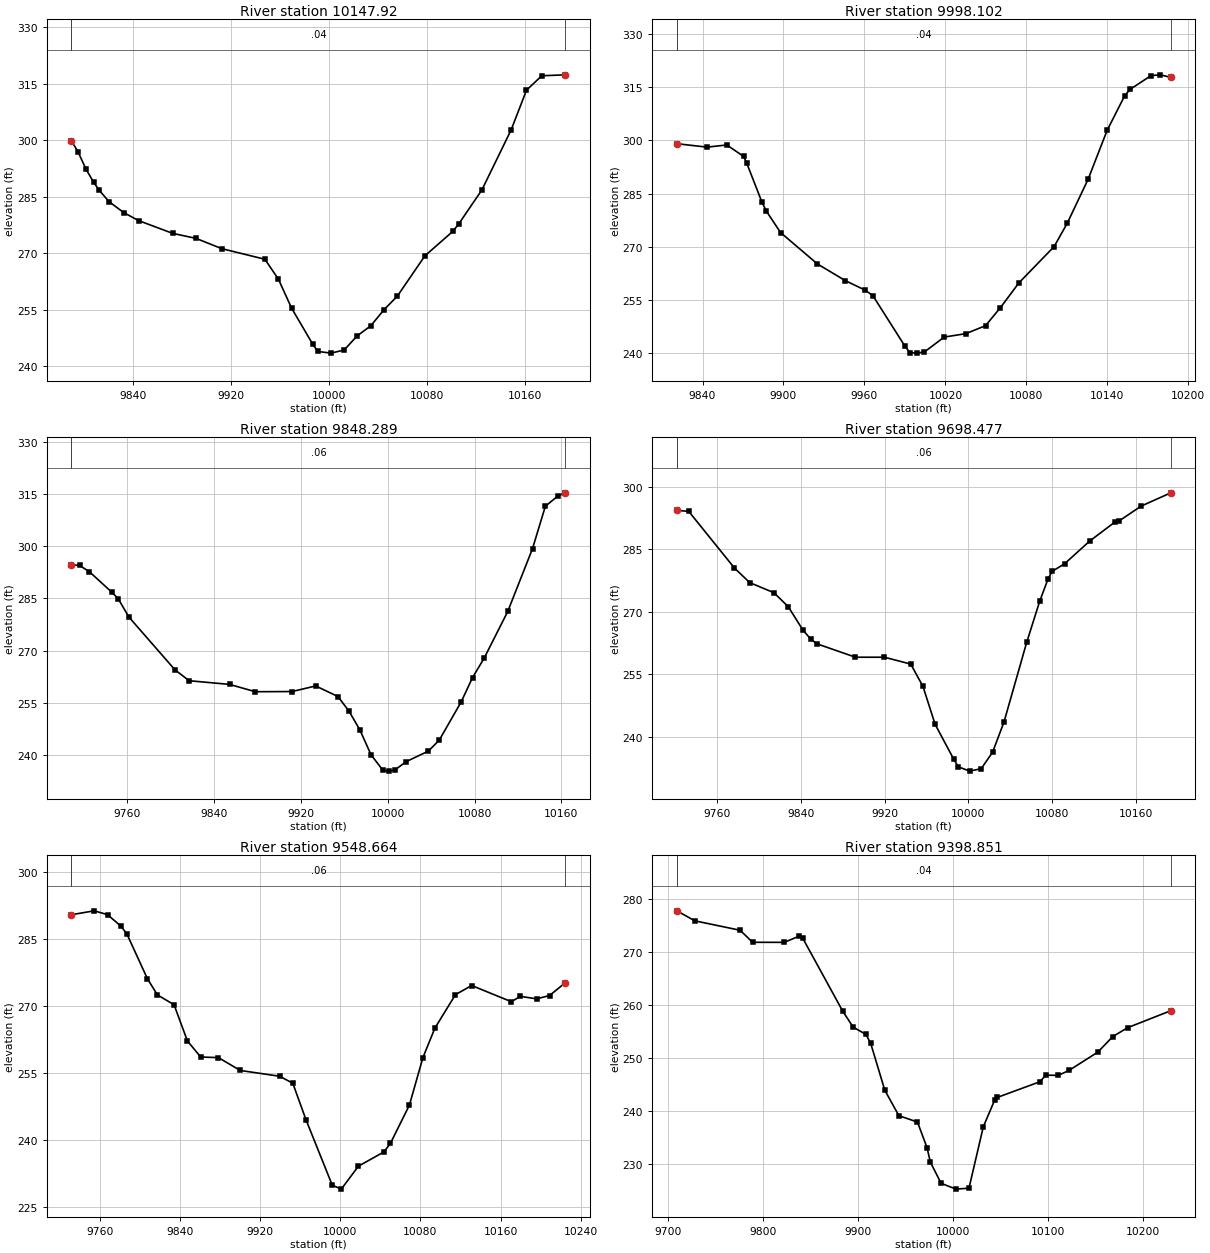
Type RM Length L Ch R = 1 ,10147.92,149.813000,149.813000,149.813000
XS GIS Cut Line= 6
803460.776850154792892.474125646803516.709773223792851.805500226
803562.588909716792825.234088299803698.802445282792767.062079101
 803730.86656133792750.222735693803810.427041935792695.312603353
#Sta/Elev= 30
9789.936299.88439795.341296.95799801.909292.35089808.141288.84339812.825286.7107
9820.541283.76429832.709280.81889844.877278.69249872.705275.30719891.818 273.974
9912.694271.25979947.961268.43919958.998263.16719969.749255.4835  9987.1245.8659
9991.253243.973910001.97243.530310012.68244.3532 10023.4248.130510034.32 250.743
10045.24255.032210056.17258.664610078.62269.334710101.42275.834510106.37 277.853
10125.18286.833410149.13302.807110161.59313.292110174.06 317.12710193.29317.3784
#Mann= 3 , 0 , 0
9789.936    0.04       09789.936    0.04       010193.29    0.04       0
#XS Ineff= 2 , 0
       0                               0
Bank Sta=9789.936,10193.29
Exp/Cntr=0.3,0.1

Type RM Length L Ch R = 1 ,9998.102,149.813000,149.813000,149.813000
XS GIS Cut Line= 6
803588.878088799793040.294342827803720.402772978792917.358793207
803740.607867934 792898.44200381803770.776405053792866.273862171
803839.903147909792784.307553663803844.693649047792779.158083072
#Sta/Elev= 30
9820.967299.06589843.359298.10319858.001298.7122 9870.42295.49779872.642293.7084
9884.111282.52829887.283280.09129897.802274.05449925.184265.18549945.848260.4948
 9960.49257.81839966.256256.26269989.772242.16919993.638240.2481    9999240.0746
10004.45240.402710019.08 244.591 10035.1245.559910049.72247.797410060.82252.9086
10074.45259.856210100.61270.107610110.35 276.70110125.86289.139110139.85302.8216
10152.93312.616410156.89 314.387 10172.4318.2494 10179.1318.472710187.04317.7803
#Mann= 3 , 0 , 0
9820.967    0.04       09820.967    0.04       010187.04    0.04       0
#XS Ineff= 2 , 0
       0                               0
Bank Sta=9820.967,10187.04
Exp/Cntr=0.3,0.1

Type RM Length L Ch R = 1 ,9848.289,149.812900,149.812900,149.812900
XS GIS Cut Line= 6
803719.725462372793206.960980167803814.479399648793092.776589888
803848.075243848793030.906758257803855.254376337792996.950471982
 803838.39975927792896.452532537803881.572951372792809.786656201
#Sta/Elev= 30
9708.414294.69449716.021294.47359725.013292.68759745.974286.71389751.476284.9719
9761.467279.64539803.846264.50119816.938261.35669854.174260.30039877.961258.1946
9911.837258.24299933.607 259.8569954.148 256.8039964.425252.53569974.299247.2187
9984.564 240.0969995.411235.6542   10001235.371610006.36235.654210017.05238.1122
10037.45241.129310047.47244.2818 10067.7 255.29310078.13262.255710088.86267.8477
10110.58281.258410133.43299.332410145.25 311.50310157.32314.572410163.62315.3574
#Mann= 3 , 0 , 0
9708.414    0.06       09708.414    0.06       010163.62    0.06       0
#XS Ineff= 2 , 0
       0                               0
Bank Sta=9708.414,10163.62
Exp/Cntr=0.3,0.1

Type RM Length L Ch R = 1 ,9698.477,149.813000,149.813000,149.813000
XS GIS Cut Line= 6
803737.016293023793232.426973428803875.261342694793089.589824776
803912.583502315793063.732218079804007.342488078 793017.88918452
804068.378421082792977.501373303804107.296205572792946.779318516
#Sta/Elev= 30
9721.224294.37769732.553294.15329776.268280.53549790.878 277.0249814.119274.5848
9827.836271.21089841.553265.70759849.318263.41579855.269262.30469892.022259.0895
9919.697259.09099944.891257.4411 9956.63  252.069968.194242.97179985.985234.6019
9990.309232.759510001.33231.712810012.27232.293610023.22 236.26910034.17243.5892
10055.76262.627410068.18272.495910076.07277.801310080.02279.716410092.01281.5373
10115.99286.994810139.98291.538910144.03291.8122 10165.2295.401110193.61298.5996
#Mann= 3 , 0 , 0
9721.224    0.06       09721.224    0.06       010193.61    0.06       0
#XS Ineff= 2 , 0
       0                               0
Bank Sta=9721.224,10193.61
Exp/Cntr=0.3,0.1

Type RM Length L Ch R = 1 ,9548.664,149.813000,149.813000,149.813000
XS GIS Cut Line= 6
803817.855905736793351.487825628803923.318123189793259.276148386
804020.346952855793177.042139169804021.874546816793175.751226047
804036.374664666793163.619582703804197.362307714793037.360084093
#Sta/Elev= 30
9731.721  290.349754.494291.20949767.778290.35339781.061287.80539787.154286.0182
9807.628276.00969817.539272.41799834.195270.20329847.478262.11889860.762 258.515
9878.425258.38759900.232255.51289939.558254.21679952.666252.64799965.774244.5096
9991.991229.8679   10001228.977710018.11 234.10810043.58237.303210050.08239.2248
10068.99247.776410082.49258.409110094.41264.982910114.89272.4595 10131.1274.5076
10170.66270.891410179.71272.077310195.92271.527610208.79272.2689 10224.5275.1268
#Mann= 3 , 0 , 0
9731.721    0.06       09731.721    0.06       0 10224.5    0.06       0
#XS Ineff= 2 , 0
       0                               0
Bank Sta=9731.721,10224.5
Exp/Cntr=0.3,0.1

Type RM Length L Ch R = 1 ,9398.851,149.813000,149.813000,149.813000
XS GIS Cut Line= 6
803902.934571614 793476.79196952803953.302414735793436.748417014
 804036.51411602793365.278353512804171.485266808793241.859638031
804236.236863989793185.091180328804295.417537515793135.975629486
#Sta/Elev= 30
9709.338277.78569728.286 275.8979775.922274.11839789.104271.84749822.411271.8367
9837.759272.98349841.832272.63019883.787 258.8999894.875255.84519908.426254.4532
9913.422252.75639928.239243.93259943.057239.12519962.633237.92349972.691233.0945
9976.184230.37149987.508 226.35910003.29225.264910016.84225.444810031.97237.0453
10043.93242.088110046.79242.580910091.84245.550810097.54  246.7810110.84246.7275
10122.18247.667710152.52251.124310168.18254.049510183.84255.731310229.29 258.935
#Mann= 3 , 0 , 0
9709.338    0.04       09709.338    0.04       010229.29    0.04       0
#XS Ineff= 2 , 0
       0                               0
Bank Sta=9709.338,10229.29
Exp/Cntr=0.3,0.1

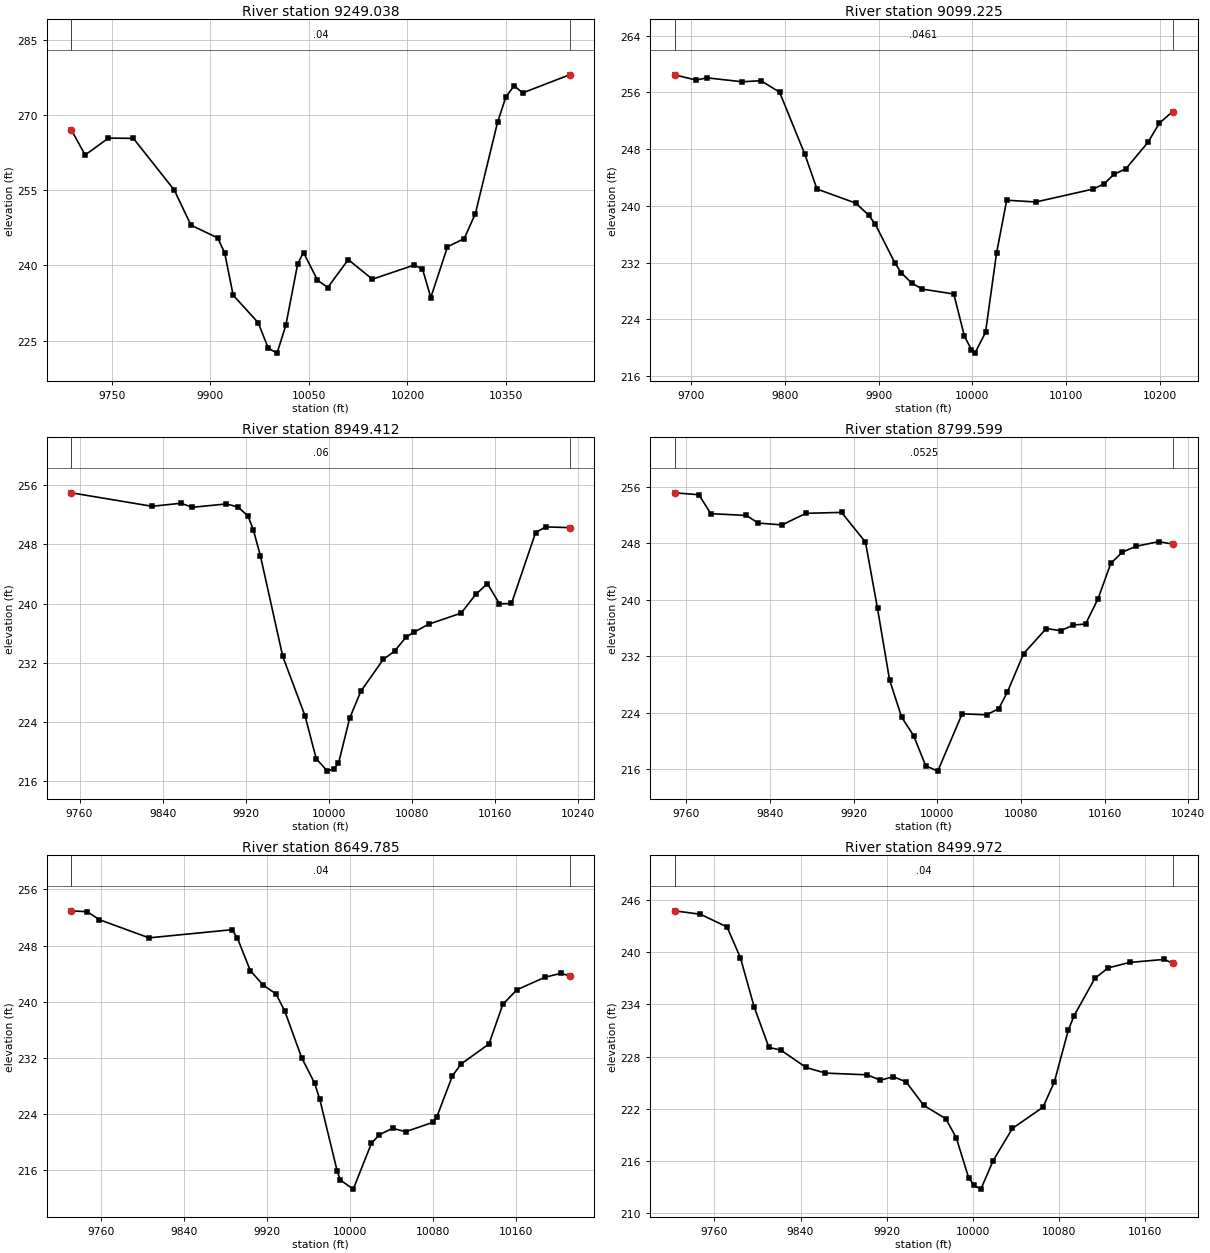
Type RM Length L Ch R = 1 ,9249.038,149.813000,149.813000,149.813000
XS GIS Cut Line= 6
803977.845443099793587.120951794804104.902135246  793496.3223702
804174.134724523793441.001365908804268.561098886 793356.97846786
804337.468377064793299.424999325804571.265709022793116.809454644
#Sta/Elev= 30
9688.937267.00359709.847262.03249745.112265.41219783.156265.36349845.241255.0636
9870.842 248.0339911.311245.49389922.043242.50229934.892234.07529972.963228.5779
9988.314223.4846 10001.7 222.49410015.12228.084610033.09240.318710041.94242.5753
10063.22237.063910078.82235.593210110.02241.1602 10146.7237.247710210.23240.0686
10222.92239.282910235.61233.590410260.98243.720410286.36 245.34610303.31 250.301
10337.12268.565310349.81273.645410362.49275.874410375.18274.426510446.58278.0433
#Mann= 3 , 0 , 0
9688.937    0.04       09688.937    0.04       010446.58    0.04       0
#XS Ineff= 2 , 0
       0                10050.21       0
Bank Sta=9688.937,10446.58
Exp/Cntr=0.3,0.1

Type RM Length L Ch R = 1 ,9099.225,149.813000,149.813000,149.813000
XS GIS Cut Line= 6
804035.127634077 793671.48635441804162.412204494793597.164330881
804241.559468149793553.667544484804361.005248723 793491.55033933
804444.353126392793443.049376438804496.965215632793409.434162487
#Sta/Elev= 30
 9682.32258.46889705.332257.73129716.912258.04219754.679257.48869774.511257.6415
9794.343256.02099821.131247.32229834.208242.36559875.734240.36629889.721 238.634
9896.497237.3761 9917.26231.96019923.899230.58749935.155229.1124 9946.41228.2514
9980.176227.56119991.432 221.634    9999219.699710002.69219.221110013.99222.1447
10025.75233.327210036.58240.784710067.68240.5355 10128.7242.357510140.27243.0781
10151.09244.445710163.73245.220510187.46248.991710199.33251.645210213.53253.2776
#Mann= 3 , 0 , 0
 9682.32  0.0461       0 9682.32  0.0461       010213.53  0.0461       0
#XS Ineff= 2 , 0
       0                               0
Bank Sta=9682.32,10213.53
Exp/Cntr=0.3,0.1

Type RM Length L Ch R = 1 ,8949.412,149.813000,149.813000,149.813000
XS GIS Cut Line= 6
804140.195303632 793757.15241884804209.583237739793722.671943817
804298.591016877793682.913930795804422.474749479 793634.23144696
804463.650526665793614.912773455804572.853684571 793552.86532547
#Sta/Elev= 30
9752.246254.97839829.729253.15799857.566253.56759868.518253.02249901.375253.4761
9912.327253.06879922.098251.85599927.213249.99879934.087246.44579955.538232.8838
9976.989224.84219987.714219.0663 9998.44217.368310004.47217.673810009.18218.4145
10019.95224.524310030.72 228.16910052.27232.462310063.11233.577510074.16235.4764
10082.06236.166310096.25237.241410127.15238.7181 10141.2241.242710152.49242.7068
10164.07239.978710175.65240.028110198.82249.597710208.45250.375410231.46250.2742
#Mann= 3 , 0 , 0
9752.246    0.06       09752.246    0.06       010231.46    0.06       0
#XS Ineff= 2 , 0
       0                               0
Bank Sta=9752.246,10231.46
Exp/Cntr=0.3,0.1

Type RM Length L Ch R = 1 ,8799.599,149.813000,149.813000,149.813000
XS GIS Cut Line= 6
804214.507421052793910.978501894804365.238964282793829.513032152
804435.487980741793789.244188952804481.738931346793761.487692657
804565.771222381793707.856781056804623.365668936793667.359156718
#Sta/Elev= 30
 9748.69 255.1499771.984254.88129783.351252.20199817.452251.94759828.819250.8668
9851.553250.61199874.288252.24729908.389252.38019931.276248.18239942.801238.7937
9954.325228.69119965.849223.41679977.373220.78219988.897216.528710000.43215.7692
10023.76223.883110047.08223.727810058.81224.6148   10067226.939710082.54232.3987
10104.18235.943410118.12 235.64510129.99236.438810141.85236.587210153.71240.1581
10165.91245.162710176.98246.756910190.36247.598110211.75248.238610225.04247.9029
#Mann= 3 , 0 , 0
 9748.69  0.0525       0 9748.69  0.0525       010225.04  0.0525       0
#XS Ineff= 2 , 0
       0                               0
Bank Sta=9748.69,10225.04
Exp/Cntr=0.3,0.1

Type RM Length L Ch R = 1 ,8649.785,149.813000,149.813000,149.813000
XS GIS Cut Line= 6
 804291.65228405794070.668368295804309.207351358794060.874163693
804387.739370683794009.345159747 804511.76564273 793918.26163511
804560.267092551793880.734065262804672.750144643793779.297301674
#Sta/Elev= 30
 9731.09252.94749746.375 252.8189758.121  251.689805.963249.10059886.262250.2637
9891.343249.04089903.748244.42739916.153 242.3729928.558241.12039936.959238.6826
9953.368232.01829965.773228.42129970.757226.12989987.656215.85839990.583214.6311
10003.09213.341110020.67219.876110028.38221.086610041.02222.003510053.66221.5112
10080.16 222.85910083.82223.653110098.75229.447810107.09231.142310134.03233.9913
10147.49239.652210160.96241.704810187.89243.486910203.28244.044210211.79243.7126
#Mann= 3 , 0 , 0
 9731.09    0.04       0 9731.09    0.04       010211.79    0.04       0
#XS Ineff= 2 , 0
       0                               0
Bank Sta=9731.09,10211.79
Exp/Cntr=0.3,0.1

Type RM Length L Ch R = 1 ,8499.972,149.813000,149.813000,149.813000
XS GIS Cut Line= 6
804444.402320496 794213.93521795804503.065142835794173.757442762
804540.159639351794138.887906725804577.179733655794093.847603722
804671.453118665793935.542403905804730.154292609793857.836866371
#Sta/Elev= 30
9723.063244.76999747.133244.37469771.777242.91249784.216239.35719796.904233.7272
9810.628229.04729821.635228.74199845.159226.73679863.136226.08799901.969225.8896
9914.033225.27119925.982225.66989937.931225.08619954.285222.37559974.744220.8381
9984.445218.66219995.904214.0678   10001213.157310007.34212.732810018.75216.0267
10036.64219.727610064.95222.1612 10075.5225.073510088.47231.042910093.89232.7086
10113.09 236.995 10125.4238.199810145.33238.828710177.18239.174110185.24238.7581
#Mann= 3 , 0 , 0
9723.063    0.04       09723.063    0.04       010185.24    0.04       0
#XS Ineff= 2 , 0
       0                               0
Bank Sta=9723.063,10185.24
Exp/Cntr=0.3,0.1

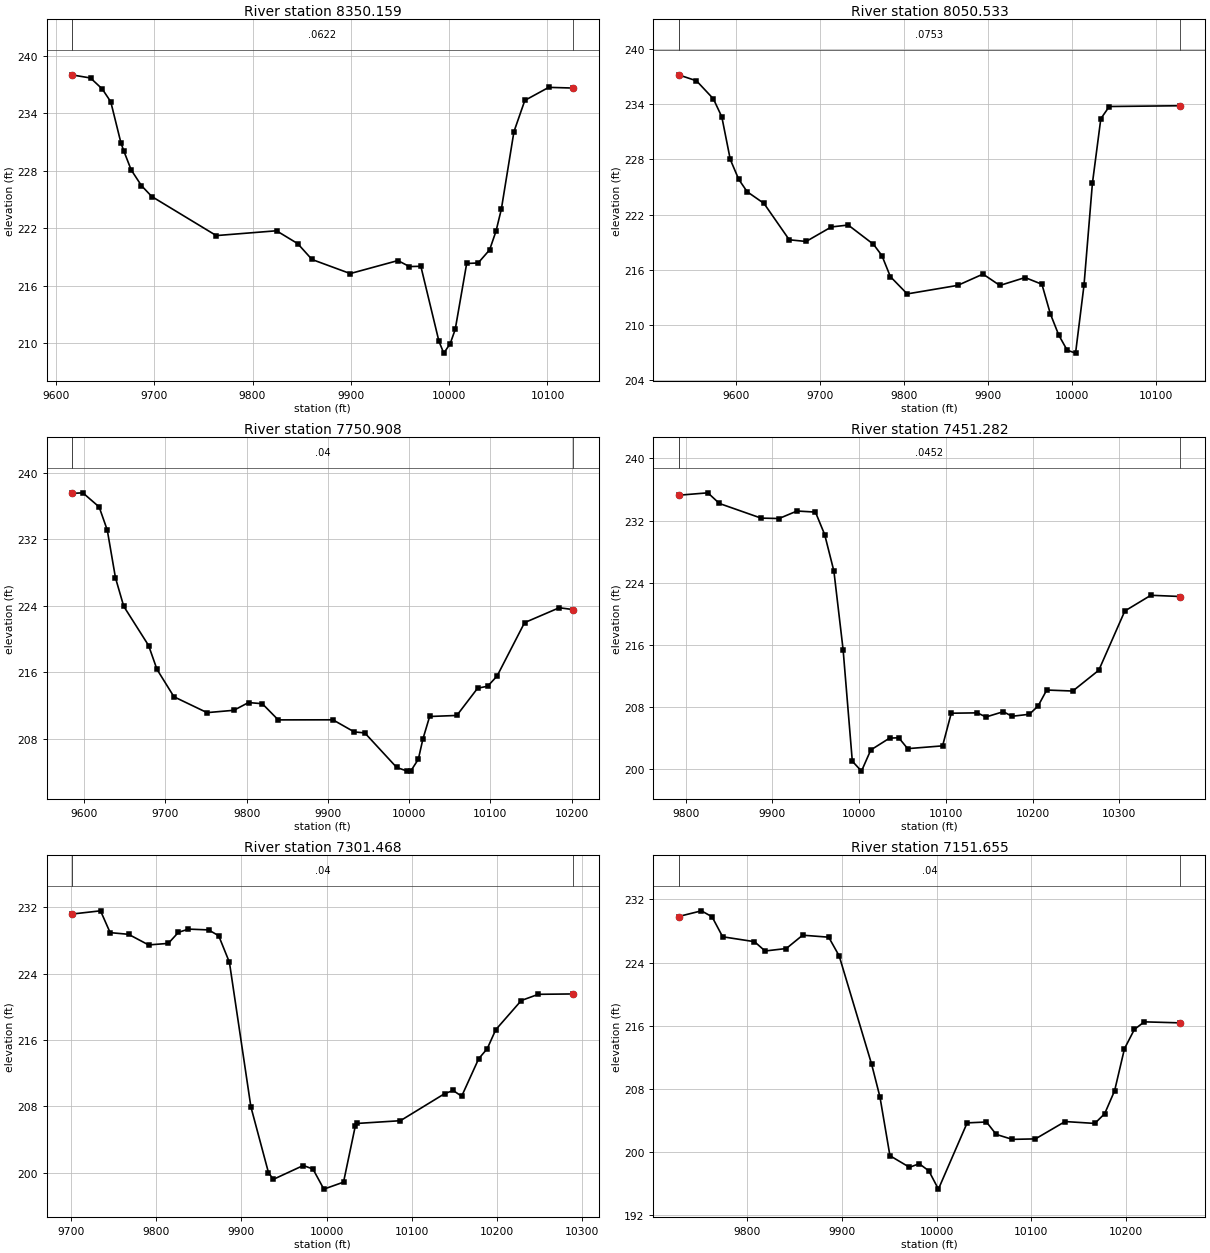
Type RM Length L Ch R = 1 ,8350.159,299.626000,299.626000,299.626000
XS GIS Cut Line= 6
804466.354643499794302.476254032804546.622685835794280.568980929
804594.587540684794260.427678414804646.548268733 794227.44761269
804708.725435246794161.837875282804829.914547374793974.910884344
#Sta/Elev= 30
9615.971238.01629635.179237.68589647.096236.54319655.782235.20079666.084 230.924
9669.226230.01989676.521228.09639687.017 226.4469697.514225.31379763.113 221.237
9824.368221.73879845.915 220.3989860.461218.74289899.353217.27279947.866218.6294
9959.528218.00369971.189218.03349989.606210.19929994.511208.9685   10001209.9452
10006.15211.441110017.81218.325710029.46218.377910041.12219.744210047.62221.6905
10053.07223.988810065.88232.078610076.97235.347110101.28236.708410126.38236.6344
#Mann= 3 , 0 , 0
9615.971  0.0622       09615.971  0.0622       010126.38  0.0622       0
#XS Ineff= 2 , 0
       09942.256                       0
Bank Sta=9615.971,10126.38
Exp/Cntr=0.3,0.1

Type RM Length L Ch R = 1 ,8050.533,299.626000,299.626000,299.626000
XS GIS Cut Line= 6
804473.765896109794332.368306218804541.429741829794325.791424083
804852.939181467794305.543863677804971.338487048794301.304765251
805050.336982098794292.622662234805068.802815673794289.203923188
#Sta/Elev= 30
9531.984237.22019553.318236.56859573.412 234.604 9583.46232.63469593.507228.0019
9603.545225.83789613.566224.48489633.608223.20699663.671219.24519683.713219.0618
9713.777220.64539733.819220.85159763.882218.74979773.903217.52159783.924215.2334
9803.967213.34759864.093214.27779894.156215.50769914.195214.26969944.211215.1307
9964.221214.39859974.227211.18589984.232208.86339994.237 207.21610004.24206.8948
10014.25214.274310024.27225.389410034.29232.438810044.35233.768110128.86233.8526
#Mann= 3 , 0 , 0
9531.984  0.0753       09531.984  0.0753       010128.86  0.0753       0
#XS Ineff= 2 , 0
       09887.757                       0
Bank Sta=9531.984,10128.86
Exp/Cntr=0.3,0.1

Type RM Length L Ch R = 1 ,7750.908,299.626000,299.626000,299.626000
XS GIS Cut Line= 6
 804481.24274193794362.524917685  804594.3030165794379.721282523
804662.638851382794409.219474273804730.423420102794460.872334546
804875.584369396794617.276134019804991.905851003794671.869575694
#Sta/Elev= 30
9584.458237.49239598.218237.56259618.316235.87019628.369233.08119638.445227.3568
9648.598223.93899679.225219.22659689.551 216.3619710.477213.06849751.206 211.165
9784.189211.44699802.269212.37539819.238212.23769838.844210.29439906.213210.3028
9932.383 208.8539945.469208.72819984.724204.58239997.809204.140410002.35204.1932
10011.39 205.56910017.01207.996410025.31210.701410058.76210.825610084.42214.1013
10096.77214.336110108.33215.556510142.22221.973610184.92223.762210202.35223.5368
#Mann= 3 , 0 , 0
9584.458    0.04       09584.458    0.04       010202.35    0.04       0
#XS Ineff= 2 , 0
       09808.988                       0
Bank Sta=9584.458,10202.35
Exp/Cntr=0.3,0.1

Type RM Length L Ch R = 1 ,7451.282,149.813000,149.813000,149.813000
XS GIS Cut Line= 6
804421.743971109794796.590615869804468.112644523794788.102917492
804554.809997886 794766.75433372804660.888142318794726.826030701
804684.969266772794721.338529706804988.960733414794707.412830636
#Sta/Elev= 30
9791.683235.26939825.491235.57889838.822234.20799886.874 232.3259907.592232.2723
9928.335233.23889949.602233.10079960.235230.21389970.868225.51939981.501215.4215
9992.134201.049510002.72199.775210013.46202.499610035.13204.022610045.73204.0658
10055.99202.667210096.26 203.02610106.27207.224610136.31207.272810146.32206.7426
10166.34207.422510176.35206.830610196.37207.090610206.38208.143110216.39210.2081
10246.43210.079610276.46212.754210306.49220.376410336.53 222.39810370.52222.2404
#Mann= 3 , 0 , 0
9791.683  0.0452       09791.683  0.0452       010370.52  0.0452       0
#XS Ineff= 2 , 0
       0                               0
Bank Sta=9791.683,10370.52
Exp/Cntr=0.3,0.1

Type RM Length L Ch R = 1 ,7301.468,149.813000,149.813000,149.813000
XS GIS Cut Line= 6
 804504.65474222794995.388032938804698.411807324794877.670281588
804770.978659385794786.368692729804812.794915351794758.988792038
804869.404434419 794749.13216508805006.160733737 794750.69069191
#Sta/Elev= 30
9700.726231.16519734.641231.55769745.931228.93229767.541 228.7299791.093227.4515
9814.228227.63759826.049228.9665 9837.87229.35669861.512229.26079873.358228.5554
9885.953225.35549911.143207.96029931.773200.04319937.449199.22579972.642200.8943
9983.977200.47359996.801198.050810019.89198.8925 10033.8205.694110035.72205.9585
10086.66206.288810138.51209.541410148.55 209.92610158.57209.235410178.57213.7554
10188.57214.955210198.57217.242210228.57220.760410248.57221.506310289.74 221.551
#Mann= 3 , 0 , 0
9700.726    0.04       09700.726    0.04       010289.74    0.04       0
#XS Ineff= 2 , 0
       0                               0
Bank Sta=9700.726,10289.74
Exp/Cntr=0.3,0.1

Type RM Length L Ch R = 1 ,7151.655,149.813000,149.813000,149.813000
XS GIS Cut Line= 6
804533.385721055795064.277084456804682.379788331794988.825706792
 804729.65913797794969.854885327804763.508655691794960.943219966
804861.607439808794942.588974399805031.431645877794890.423970662
#Sta/Elev= 30
9727.151229.83749751.379230.55949762.588229.79889773.797227.26379807.425226.6442
9818.634225.46129841.052225.77489858.359227.46679885.889227.21329896.984224.8339
9931.288 211.0799940.084 206.9259950.627 199.4769971.308198.00539981.619198.4574
9991.755197.552410001.88195.233810032.25 203.64310052.68203.755610062.94202.1822
10079.96201.550810104.43201.610510135.81203.8129 10167.2203.573210177.66204.8101
10188.12207.714210198.58  213.0610209.04215.5042 10219.5216.467810257.62216.3368
#Mann= 3 , 0 , 0
9727.151    0.04       09727.151    0.04       010257.62    0.04       0
#XS Ineff= 2 , 0
       0                               0
Bank Sta=9727.151,10257.62
Exp/Cntr=0.3,0.1

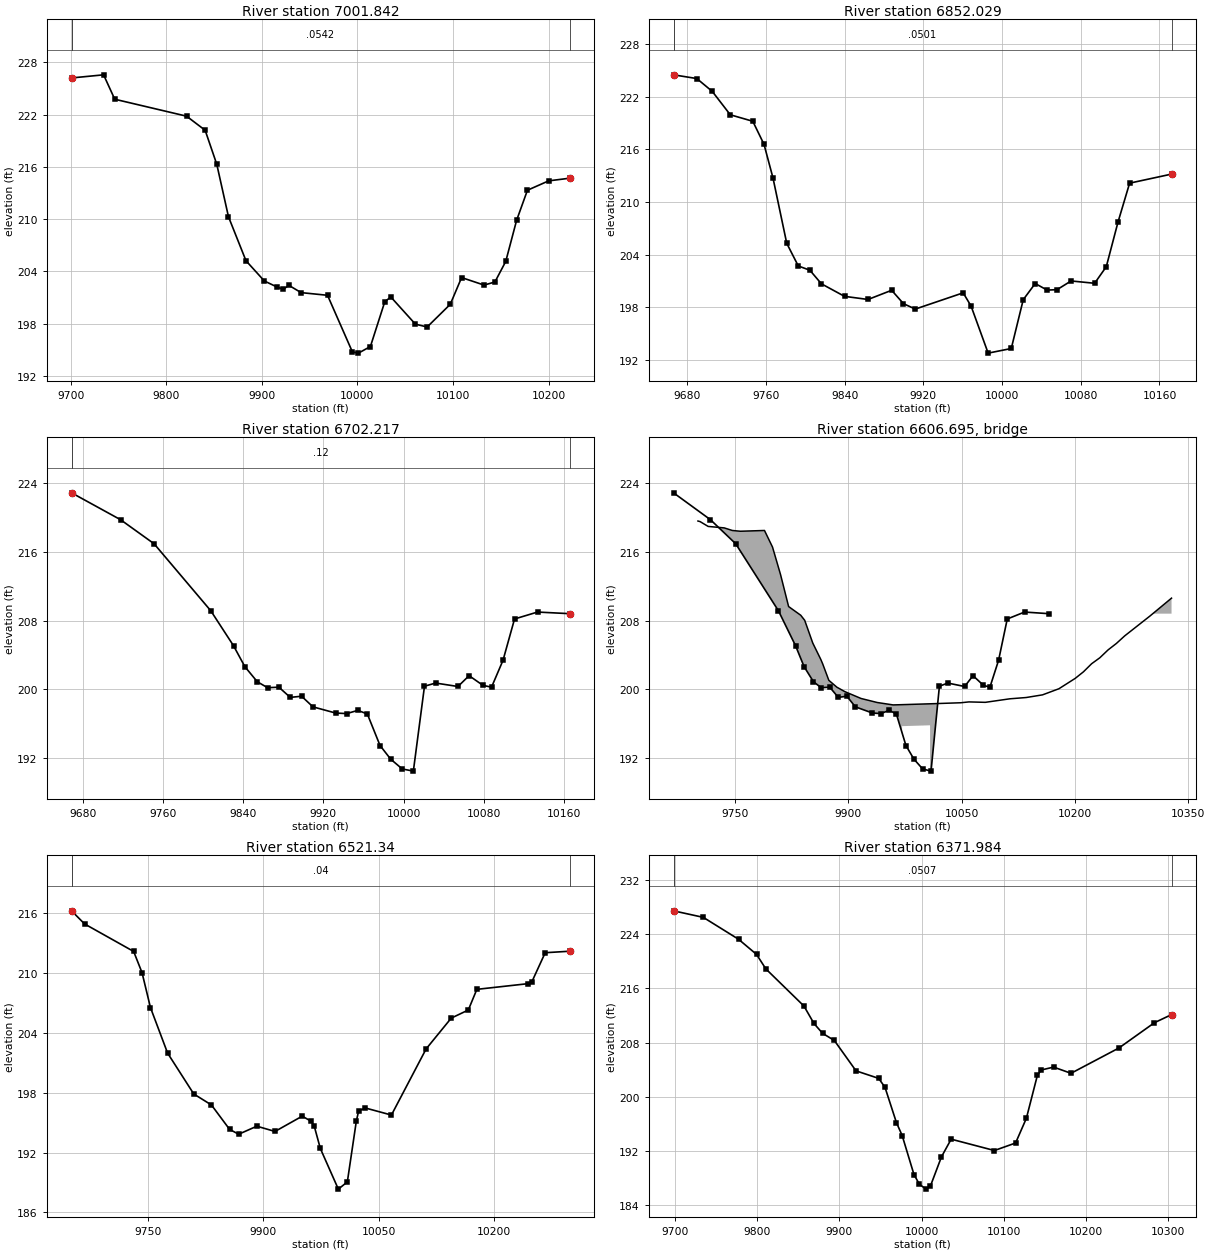
Type RM Length L Ch R = 1 ,7001.842,149.813000,149.813000,149.813000
XS GIS Cut Line= 6
804615.353047155795255.770374773804712.153818283795199.832348502
804770.010438915795159.412591255804920.571866998795033.206816533
804961.198140219795007.267295938  805044.9990289794965.443617888
#Sta/Elev= 30
9700.957226.19999734.461226.55849746.128 223.7589821.252221.81299840.684220.1962
9852.882216.27849865.081210.27219883.392205.22369902.605202.89789915.423202.2295
9922.416201.94339928.241202.39919941.059201.56249968.702201.25559994.722194.7533
   10001194.617710013.56195.376810028.61 200.52210034.93201.0603 10060.6197.9427
10072.93 197.61710097.08200.220810108.94203.290210132.47202.4274 10143.8202.7827
10155.13205.146510166.47209.8561 10177.8213.311910199.97214.387610221.87214.6923
#Mann= 3 , 0 , 0
9700.957  0.0542       09700.957  0.0542       010221.87  0.0542       0
#XS Ineff= 2 , 0
       09859.234                       0
Bank Sta=9700.957,10221.87
Exp/Cntr=0.3,0.1

Type RM Length L Ch R = 1 ,6852.029,149.813000,149.813000,149.813000
XS GIS Cut Line= 6
804673.730444265795372.525168984804703.558554493795358.018328745
804768.742799881795321.791570796804829.532583996795284.301456267
805023.030758683 795151.33401704805101.566627969795102.737181955
#Sta/Elev= 30
9665.942224.50929689.594224.08529705.324222.61869723.641219.95419746.522219.2139
9757.963216.57229767.081212.73559781.037205.29819792.786202.71389804.535202.2323
9816.283200.68169839.781199.25239863.689198.89499887.718199.94359899.732198.4146
9911.746   197.89960.415 199.6529968.475198.13869985.817192.777610009.34193.3056
 10021.5198.873510033.66200.713310045.82199.964210055.88200.014210070.14201.0069
10094.09200.740910105.94202.634510117.79207.694410129.65212.157210172.27213.1885
#Mann= 3 , 0 , 0
9665.942  0.0501       09665.942  0.0501       010172.27  0.0501       0
#XS Ineff= 2 , 0
       09880.469        10110.69       0
Bank Sta=9665.942,10172.27
Exp/Cntr=0.3,0.1

Type RM Length L Ch R = 1 ,6702.217,180.876900,180.876900,180.876900
XS GIS Cut Line= 6
804730.423378037795477.772160039804792.025205032795449.974238894
804963.215972871 795359.43768205805036.347659429795324.691281513
805100.856500038795293.344302577805172.677066923795252.715562404
#Sta/Elev= 30
9668.946222.85889717.851 219.7289751.207216.93429807.769209.13589830.394205.0753
9841.706202.63949854.119200.88219864.331200.19439875.643200.25049886.956199.0651
9898.268199.2003 9909.58197.96429932.162197.24599943.236197.1808 9954.31197.5538
9963.799 197.1379976.457193.46839987.081191.87889998.604190.741810009.67190.4886
10020.77200.366310031.89 200.73210054.13200.332710065.25201.591510079.09200.4622
10087.62200.254310099.08203.386910110.54208.185210133.46208.991710165.39208.8033
#Mann= 3 , 0 , 0
9668.946    0.12       09668.946    0.12       010165.39    0.12       0
#XS Ineff= 2 , 0
       09931.824        10045.98       0
Bank Sta=9668.946,10165.39
Exp/Cntr=0.3,0.1

Type RM Length L Ch R = 3 ,6606.695,,,
BEGIN DESCRIPTION:
END DESCRIPTION:
Bridge Culvert--1,0,-1,-1, 0
Deck Dist Width WeirC Skew NumUp NumDn MinLoCord MaxHiCord MaxSubmerge Is_Ogee
77.938450,25.000000,2.6,0, 41, 41, , , 0.95, 0, 0,0,,
 9701.26 9704.11 9714.76 9736.05 9746.70 9757.35 9789.29 9799.93 9810.58 9821.23
 9837.25 9842.52 9853.17 9863.82 9866.38 9874.46 9885.11 9895.51 9917.05 9938.49
 9959.51 9971.38 9971.3810008.3810008.3810048.9010059.8110081.4610113.9310135.58
10157.2310178.8810200.5310211.3610222.1810233.0010243.9810254.9710265.9610299.24
10327.92
  219.58  219.51  218.95  218.78  218.48  218.39  218.48  216.55  213.34  209.63
  208.62  208.03  205.39  203.48  202.95  201.05  200.25  199.74  198.94  198.47
  198.19  198.22  198.22  198.32  198.32  198.44  198.54  198.49  198.90  199.05
  199.36  200.07  201.28  202.04  202.98  203.67  204.59  205.34  206.22  208.52
  210.61
 -780.42 -780.49 -781.05 -781.22 -781.52 -781.61 -781.52 -783.45 -786.66 -790.37
 -791.38 -791.97 -794.61 -796.52 -797.05 -798.95 -799.75 -800.26 -801.06 -801.53
 -801.81 -801.78  195.72  195.82 -801.68 -801.56 -801.46 -801.51 -801.10 -800.95
 -800.64 -799.93 -798.72 -797.96 -797.02 -796.33 -795.41 -794.66 -793.78 -791.48
 -789.39
 9701.26 9704.11 9714.76 9736.05 9746.70 9757.35 9789.29 9799.93 9810.58 9821.23
 9837.25 9842.52 9853.17 9863.82 9866.38 9874.46 9885.11 9895.51 9917.05 9938.49
 9959.51 9971.40 9971.4010008.4010008.4010048.9010059.8110081.4610113.9310135.58
10157.2310178.8810200.5310211.3610222.1810233.0010243.9810254.9710265.9610299.24
10327.92
  219.58  219.51  218.95  218.78  218.48  218.39  218.48  216.55  213.34  209.63
  208.62  208.03  205.39  203.48  202.95  201.05  200.25  199.74  198.94  198.47
  198.19  198.22  198.22  198.32  198.32  198.44  198.54  198.49  198.90  199.05
  199.36  200.07  201.28  202.04  202.98  203.67  204.59  205.34  206.22  208.52
  210.61
 -780.42 -780.49 -781.05 -781.22 -781.52 -781.61 -781.52 -783.45 -786.66 -790.37
 -791.38 -791.97 -794.61 -796.52 -797.05 -798.95 -799.75 -800.26 -801.06 -801.53
 -801.81 -801.78  195.72  195.82 -801.68 -801.56 -801.46 -801.51 -801.10 -800.95
 -800.64 -799.93 -798.72 -797.96 -797.02 -796.33 -795.41 -794.66 -793.78 -791.48
 -789.39
BR Coef=-1 , 0 , 0 ,, 0 ,,,0.8,0,1,0,
WSPro=,,,, 1 ,,,, 0 ,,,, 0 ,,,,-1 ,-1 ,-1 , 0 , 0 , 0 , 0 , 0
BC Design=,, 0 ,, 0 ,,,,,,

Type RM Length L Ch R = 1 , 6521.34,149.356000,149.356000,149.356000
XS GIS Cut Line= 6
 804818.95002525795639.209259386804877.906210523795619.793389211
804924.746754531795599.095891904804978.194947411795570.443269092
 805165.00000003795454.380515382805393.509123729795343.609875286
#Sta/Elev= 30
9650.353216.26439667.248214.95039731.113212.18739742.045210.05259752.978206.5566
9775.268201.98589809.306197.88439832.314196.78019855.932194.32959867.741 193.844
9891.359  194.659914.977194.12219950.404195.65739962.212 195.1339966.131 194.628
 9973.95192.41479997.369188.334210009.08189.058210020.79195.163310023.79196.1795
 10032.5196.477910066.43195.768810111.56 202.40510144.22205.495210166.45206.3115
10177.56208.383710244.24208.954810249.11209.138110266.47212.060510298.15212.2097
#Mann= 3 , 0 , 0
9650.353    0.04       09650.353    0.04       010298.15    0.04       0
#XS Ineff= 2 , 0
       09951.859        10040.14       0
Bank Sta=9650.353,10298.15
Exp/Cntr=0.3,0.1

Type RM Length L Ch R = 1 ,6371.984,149.355900,149.355900,149.355900
XS GIS Cut Line= 6
804950.415492892795761.747401652805043.188819244795727.902256337
805126.261668091795675.625822381805200.795206117795603.752046414
805311.095321963795473.453072189805411.365253701795384.261064789
#Sta/Elev= 30
9698.128227.44059734.324226.47799777.195223.25239799.107221.01759810.458218.8784
9856.826213.39999869.013210.82849879.512209.37519893.808208.32269920.193203.8434
9947.677202.73769955.396201.4319 9969.35196.21539976.353 194.3039990.691188.5577
9997.259187.128410005.31 186.40410010.78186.873810024.16191.165710035.95193.7706
10088.58192.095810114.35 193.20610127.51196.862210140.91203.203110145.57203.9713
 10160.6204.3978 10181.8203.484710240.13207.216610283.37210.947410304.11212.1353
#Mann= 3 , 0 , 0
9698.128  0.0507       09698.128  0.0507       010304.11  0.0507       0
#XS Ineff= 2 , 0
       09927.433                       0
Bank Sta=9698.128,10304.11
Exp/Cntr=0.3,0.1