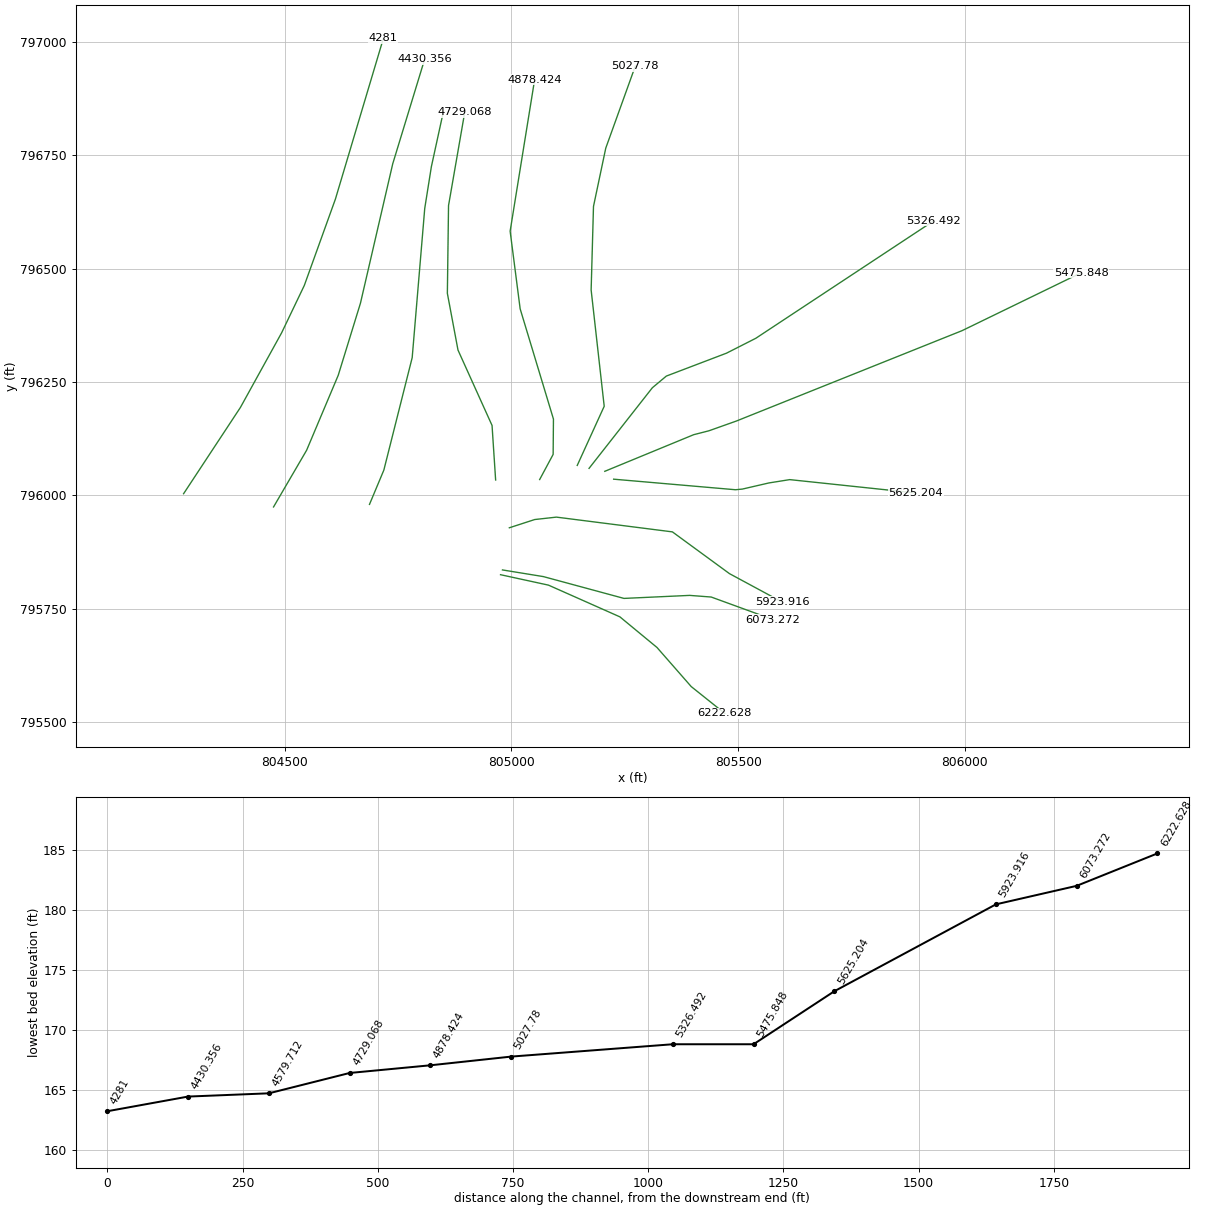
HEC-RAS study 17439_ras.prj: 17439

--- 17439_ras.g01 (geometry) --- (continued)

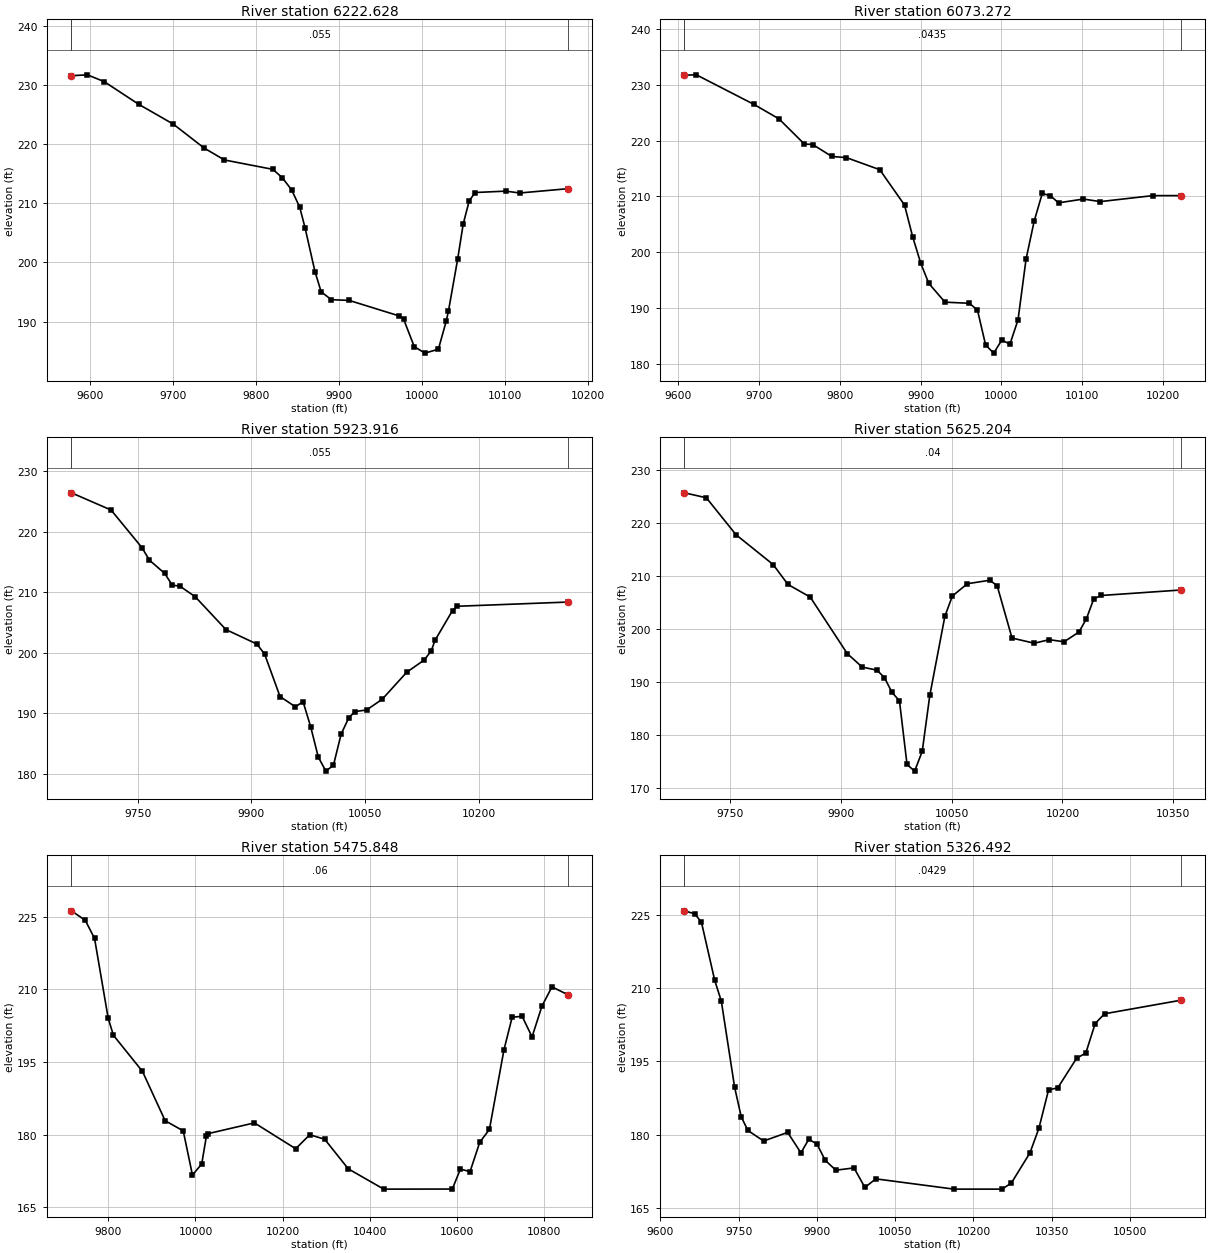
Type RM Length L Ch R = 1 ,6222.628,149.356000,149.356000,149.356000
XS GIS Cut Line= 6
804976.030447196795824.869967612805081.738657425795801.882184526
 805239.26144745795731.920982281805321.067956103795664.392459661
805396.548760562 795578.17037281805470.570764132795519.048077867
#Sta/Elev= 30
9578.139231.52679597.285231.67679617.535230.52669658.846226.71939700.601223.3601
 9737.85219.30679762.236217.3008 9820.31215.72559831.661214.33079843.012212.2517
9852.692209.3554  9859.2205.8351 9871.11198.45119878.539195.05069890.827193.7207
9912.197193.59849971.751191.00849977.664190.45629990.576185.792310003.37184.6993
 10019.6185.361610028.95190.0769 10031.6191.7295 10042.7200.512910049.48206.5252
 10056.7210.407710063.77211.811510100.73212.044410117.44211.730810175.07 212.452
#Mann= 3 , 0 , 0
9578.139   0.055       09578.139   0.055       010175.07   0.055       0
#XS Ineff= 2 , 0
       0                               0
Bank Sta=9578.139,10175.07
Exp/Cntr=0.3,0.1

Type RM Length L Ch R = 1 ,6073.272,149.356000,149.356000,149.356000
XS GIS Cut Line= 6
804980.297095744795835.384208676805070.519503804 795820.68913716
805248.243083292 795772.59207056805393.049908925795779.250128377
805440.665628612795775.623105168805577.038429602795725.908286817
#Sta/Elev= 30
9607.691231.6881 9622.45231.75059693.591226.47349724.737223.8738 9756.01219.3903
9766.434219.29229790.176217.15259808.132216.95049849.449214.79079880.127208.4724
9890.205202.80199900.212 198.0619910.219194.45369930.247191.10439960.405190.9066
9970.457189.68149980.509183.44839990.562181.993810000.59184.3406 10010.6183.5898
10020.61187.919110030.61198.819410040.62205.586610050.62210.536510060.68210.1416
10070.76208.8648 10101.5209.540610122.48209.083510187.19210.148810221.92  210.16
#Mann= 3 , 0 , 0
9607.691  0.0435       09607.691  0.0435       010221.92  0.0435       0
#XS Ineff= 2 , 0
       0                               0
Bank Sta=9607.691,10221.92
Exp/Cntr=0.3,0.1

Type RM Length L Ch R = 1 ,5923.916,298.711900,298.711900,298.711900
XS GIS Cut Line= 6
 804995.47115007795928.376683202805051.524188232795946.565429689
 805099.28326772795951.866559229805355.040508787795919.322453542
805481.017329453795827.152636588 805597.15237317 795764.53982923
#Sta/Elev= 30
9662.855226.43729715.104223.59119755.658217.40069765.676 215.3039785.703213.1324
9795.716211.18039805.729211.02179825.898209.27739866.503203.83989907.245 201.453
9917.431199.80879937.802192.7773 9958.11191.07499968.154191.93029978.198187.7941
9988.219 182.7839998.221180.448810008.23181.416110018.31186.538810028.57189.3011
10037.04190.299710051.86190.550310072.43192.311610104.79196.780510127.91198.8111
10137.14 200.31210142.26202.083810165.23206.989610171.33207.690410316.98208.3858
#Mann= 3 , 0 , 0
9662.855   0.055       09662.855   0.055       010316.98   0.055       0
#XS Ineff= 2 , 0
       0                               0
Bank Sta=9662.855,10316.98
Exp/Cntr=0.3,0.1

Type RM Length L Ch R = 1 ,5625.204,149.356000,149.356000,149.356000
XS GIS Cut Line= 6
805225.505872279796035.537830636805494.172689855796012.246881813
805509.442257136796013.726405472805567.860640407 796027.22203286
805613.824173301796034.562048674805891.738511205796005.155886203
#Sta/Elev= 30
9688.809225.60759718.408224.67349758.549217.71549808.726212.10189828.797208.3533
9858.903 205.9729909.079195.3186 9929.15192.79829949.244192.20859959.332190.8055
9969.378188.04029979.551186.45469989.824174.449410000.09173.201210010.35176.9078
10020.61187.460510041.03202.377310051.16206.177310071.41208.491510101.64209.1436
10111.69208.122810131.81198.258610161.97197.285710182.09197.9536 10202.2197.5593
10222.31199.387610232.36201.871610242.42205.658910252.48206.276710359.81207.3042
#Mann= 3 , 0 , 0
9688.809    0.04       09688.809    0.04       010359.81    0.04       0
#XS Ineff= 2 , 0
       0                10064.65       0
Bank Sta=9688.809,10359.81
Exp/Cntr=0.3,0.1

Type RM Length L Ch R = 1 ,5475.848,149.356000,149.356000,149.356000
XS GIS Cut Line= 6
805205.974622309796052.898941755805401.872550815796133.611066341
805435.709741473796142.298373386805495.867518216796163.667022318
805993.747165859 796363.02840133 806256.47866106 796490.68272914
#Sta/Elev= 30
9715.352226.21689747.118224.24499768.376220.50789799.619204.05539811.638200.5365
9878.371193.07229930.455 182.897 9971.97180.80519993.088171.684910014.39173.9818
10025.08179.698610029.54180.243610135.31182.453310230.13177.116210262.41180.0068
 10296.7179.0726 10350.9172.965910432.19168.781210589.72168.798110608.19172.9066
10630.43172.396710652.66178.4455 10674.9181.104310708.25197.521510727.01204.2389
 10749.9204.464410772.78200.199910795.66206.596510818.54 210.52510854.43208.9247
#Mann= 3 , 0 , 0
9715.352    0.06       09715.352    0.06       010854.43    0.06       0
#XS Ineff= 2 , 0
       0                 10058.9       0
Bank Sta=9715.352,10854.43
Exp/Cntr=0.3,0.1

Type RM Length L Ch R = 1 ,5326.492,298.711900,298.711900,298.711900
XS GIS Cut Line= 6
 805171.25240007796059.409358412805310.809273154796237.103906527
 805341.71169132 796262.92874524805474.410699576796313.454352051
805539.000960261796346.255747303805931.172300726 796605.15359579
#Sta/Elev= 30
9645.949225.94059665.773225.32019678.488 223.6049703.919211.67019716.634207.3854
9742.065189.72419754.781183.63099767.496180.83429797.728178.66079843.788180.4315
9869.219176.23329884.208 179.0119899.803178.06279915.995174.67299936.291172.6664
 9970.96173.14089991.872169.132510012.76170.891310162.57168.781210254.65168.7812
10272.52170.010310308.26176.2203 10325.4181.258610343.99189.1745 10361.6189.5766
 10397.6 195.63610415.47  196.7610433.34202.785710451.26204.795210597.11207.5706
#Mann= 3 , 0 , 0
9645.949  0.0429       09645.949  0.0429       010597.11  0.0429       0
#XS Ineff= 2 , 0
       0                10055.45       0
Bank Sta=9645.949,10597.11
Exp/Cntr=0.3,0.1

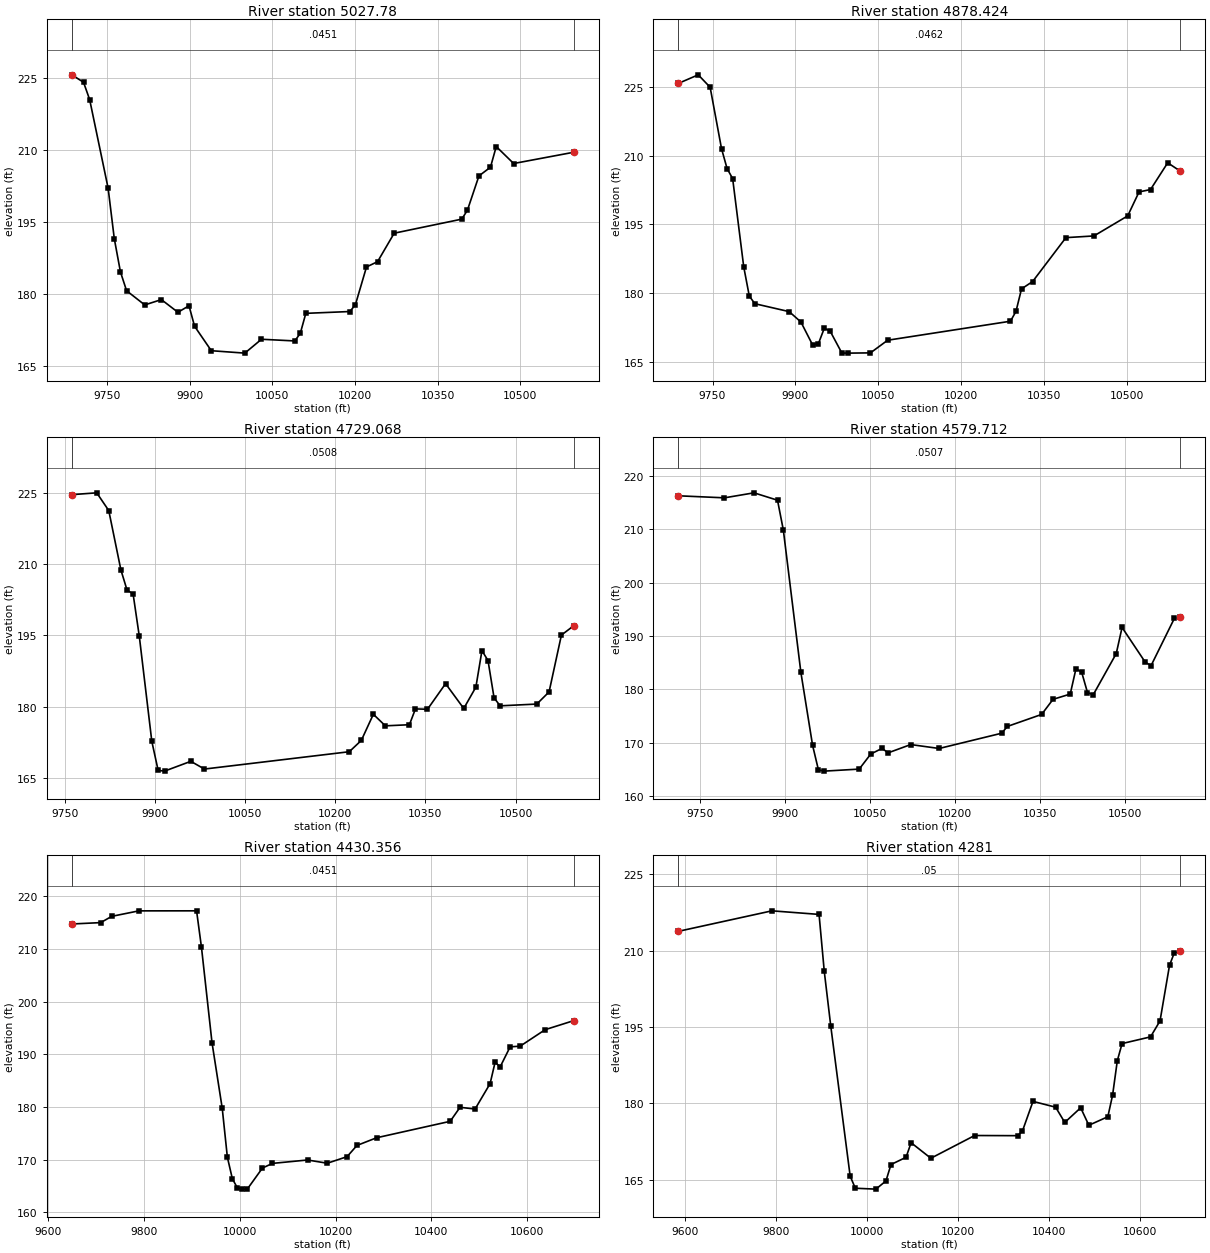
Type RM Length L Ch R = 1 , 5027.78,149.356000,149.356000,149.356000
XS GIS Cut Line= 6
805145.210733414796065.919775084805204.668975413796196.328300044
805175.851351738796452.775496736805181.038181961796637.163056985
805208.098436415796765.615367487805273.300287396796946.618146449
#Sta/Elev= 30
9685.855225.74339707.159224.20279718.324220.5798 9751.82202.12199762.985191.6313
 9774.15184.69519785.316 180.7569818.274177.79499848.458178.90469878.506176.2654
9898.632177.62219908.694173.35529939.103168.25499999.932167.751310030.16170.6419
 10090.6170.290110100.61171.877910110.62176.0418 10190.7176.420810200.71177.8782
10220.73185.708310240.79186.8042   10271192.742710393.61195.671610403.88197.5266
 10424.8204.681810445.73206.4915 10456.2210.800810487.79207.261310597.04209.6153
#Mann= 3 , 0 , 0
9685.855  0.0451       09685.855  0.0451       010597.04  0.0451       0
#XS Ineff= 2 , 0
       0                               0
Bank Sta=9685.855,10597.04
Exp/Cntr=0.3,0.1

Type RM Length L Ch R = 1 ,4878.424,149.356000,149.356000,149.356000
XS GIS Cut Line= 6
805062.329686249796034.750504546 805092.05824561796090.178213761
805092.730870134796168.097510602 805019.31965076796411.144311902
804997.209455374796582.439141033 805051.30073729796916.967938416
#Sta/Elev= 30
 9687.91225.66749724.098227.54319745.679224.83959766.289211.48789776.414207.1329
9786.419204.99169806.505185.79049816.572179.43949826.638177.77199888.781176.0529
9909.989173.80629931.196168.8146  9941.8169.10589952.404172.45089963.008171.8035
 9984.16167.05219994.519167.026210035.97167.080910067.08169.830410289.47173.9649
10299.48176.1064 10309.5 180.99710329.58182.589710389.88192.138910440.65192.5109
10501.76196.868610522.31202.080110543.07202.596310574.22 208.41710597.03206.5894
#Mann= 3 , 0 , 0
 9687.91  0.0462       0 9687.91  0.0462       010597.03  0.0462       0
#XS Ineff= 2 , 0
       0                               0
Bank Sta=9687.91,10597.03
Exp/Cntr=0.3,0.1

Type RM Length L Ch R = 1 ,4729.068,149.356000,149.356000,149.356000
XS GIS Cut Line= 6
804965.220711016796033.749381087804957.317820302796154.047938099
804882.218505934796320.281420104804858.772600592796445.376105084
804861.344516924796638.923107739804897.173109835796845.162913872
#Sta/Elev= 30
9761.706224.6863 9803.25225.07179823.266221.32519843.444208.81259853.571204.5976
9863.776 203.7239874.074194.81049894.901172.64379905.411166.5415 9916.02166.3851
 9959.77168.45279982.423166.822510223.42170.477410243.45 172.86210263.45178.3733
10283.45 175.93610323.47176.169510333.48179.505810353.54179.429410383.63184.8322
10413.87179.596310434.05184.101310444.14 191.79910454.23189.702210464.32181.8347
10474.41180.154610535.44180.528110555.83183.091710576.35195.076810597.04 197.062
#Mann= 3 , 0 , 0
9761.706  0.0508       09761.706  0.0508       010597.04  0.0508       0
#XS Ineff= 2 , 0
       0                               0
Bank Sta=9761.706,10597.04
Exp/Cntr=0.3,0.1

Type RM Length L Ch R = 1 ,4579.712,149.355900,149.355900,149.355900
XS GIS Cut Line= 6
804687.040693569795979.930256546804718.684315131796055.535473684
804781.192870905796303.518867777804808.888715204796632.794496716
804823.518705059796724.806137017804849.804711604 796845.29772129
#Sta/Elev= 30
9712.169216.24039793.631215.85849845.679216.79549887.146215.41249897.446209.8025
9928.345183.16269948.944169.52669959.244164.92099969.543164.688410031.12165.0685
10051.52167.891610071.66168.961210081.73168.097910121.93169.662610172.02168.9293
10282.23171.785810292.29173.059110352.63175.304210372.74178.131510403.06179.1165
10413.19183.876310423.31183.180710433.44179.409710443.57 178.98610484.18 186.703
10494.41191.590210535.36  185.0710545.59184.453310586.53193.272510597.07193.6398
#Mann= 3 , 0 , 0
9712.169  0.0507       09712.169  0.0507       010597.07  0.0507       0
#XS Ineff= 2 , 0
       0                               0
Bank Sta=9712.169,10597.07
Exp/Cntr=0.3,0.1

Type RM Length L Ch R = 1 ,4430.356,149.356000,149.356000,149.356000
XS GIS Cut Line= 6
804475.420188934 795974.28596127804548.372696429796099.311170176
804618.143444419796264.789676785804667.083361238796423.579394758
804738.303246856796731.111314997804808.839205623796962.187136203
#Sta/Elev= 30
9649.286214.72969709.652214.99029732.688216.17999789.336  217.229909.803217.2272
 9920.04210.29189942.009192.21879963.384179.74579974.066170.47919984.522166.3733
9994.977164.657110005.41164.417210015.87164.447810047.28168.416410068.22169.3016
10141.48169.945410182.71169.331410223.94 170.57810244.53172.702710285.51174.1624
 10439.2177.285310459.77179.945610491.14 179.618 10522.5184.437110532.96188.5156
10543.41187.596410564.33191.419110585.24 191.54410637.51194.678110697.31196.3957
#Mann= 3 , 0 , 0
9649.286  0.0451       09649.286  0.0451       010697.31  0.0451       0
#XS Ineff= 2 , 0
       0                               0
Bank Sta=9649.286,10697.31
Exp/Cntr=0.3,0.1

Type RM Length L Ch R = 1 ,    4281,0.000000,0.000000,0.000000
XS GIS Cut Line= 6
804277.077838242 796003.48974295804402.305378705796193.626737565
804493.278407902796358.387329772804543.225816876796462.636174679
804611.836681962796653.149432749804717.693372309797007.760052875
#Sta/Elev= 30
9584.927213.78439791.055217.8145 9894.66217.11149906.131 205.9219920.341195.2456
9963.076165.73879974.439163.367510019.69163.1938 10041.8164.801310052.86168.0193
10086.04169.4451 10097.1172.303810140.58169.254410236.85173.715510331.53173.6841
10341.96174.584410365.18180.413210415.02179.2732 10435.1176.282210470.06179.1596
10488.07175.726910529.81177.403110540.25181.624310550.68188.406210561.12191.7619
10623.74193.075510644.61196.214710665.48207.115410675.92209.558210689.23209.8944
#Mann= 3 , 0 , 0
9584.927    0.05       09584.927    0.05       010689.23    0.05       0
#XS Ineff= 2 , 0
       0                               0
Bank Sta=9584.927,10689.23
Exp/Cntr=0.3,0.1